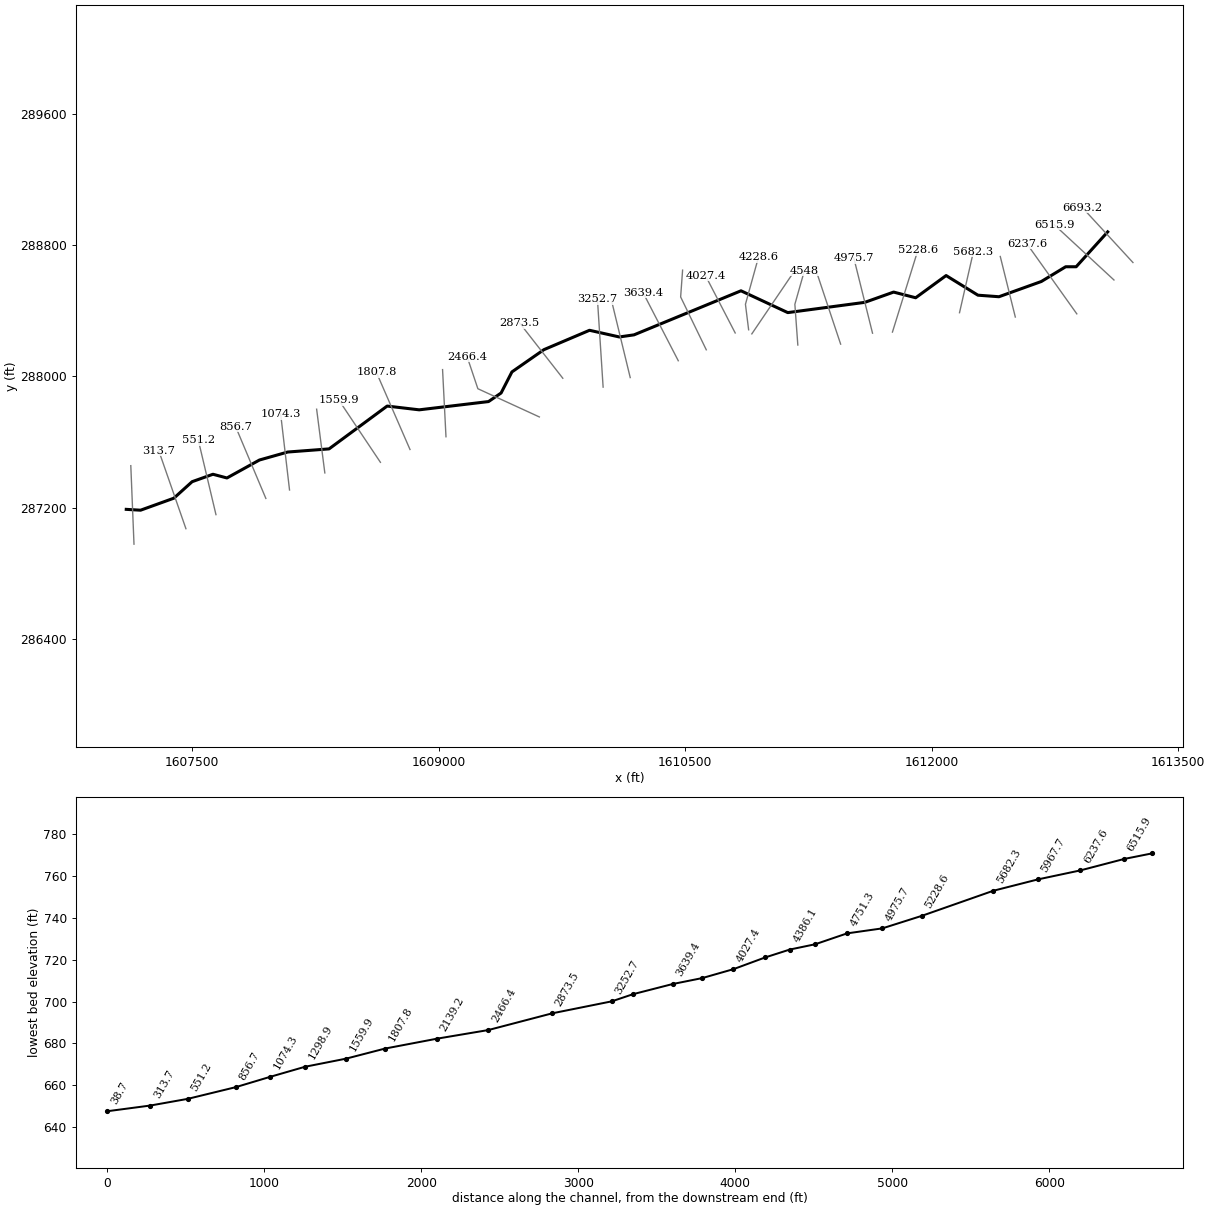
--- np13.prj (project) ---

Proj Title=np13
Current Plan=p01
Default Exp/Contr=0,0
English Units
Geom File=g01
Flow File=f01
Plan File=p01
BEGIN DESCRIPTION:
END DESCRIPTION:
DSS Export Rating Curves= 0
DSS Export Rating Curve Sorted= 0
DSS Export Volume Flow Curves= 0
DXF OffsetX= 0
DXF OffsetY= 0
DXF ScaleX= 0
DXF ScaleY= 0

--- np13.p01 (plan) ---

Plan Title=Approximate Study - 100yr
Program Version=4.00
Geom File=g01
Flow File=f01
Subcritical Flow
K Sum by GR= 0
Std Step Tol= 0.01
Critical Tol= 0.01
Num of Std Step Trials= 20
Max Error Tol= 0.3
Flow Tol Ratio= 0.001
Split Flow NTrial= 30
Split Flow Tol= 0.02
Split Flow Ratio= 0.02
Log Output Level= 0
Friction Slope Method= 1
Unsteady Friction Slope Method= 2
Unsteady Bridges Friction Slope Method= 1
Parabolic Critical Depth
Global Vel Dist= 0 , 0 , 0
Global Log Level= 0
CheckData=True
Encroach Param=-1 ,0,0, 0
Run HTab= 0
Run UNet= 0
Run PostProcess= 0
Run WQNet= 0
UNET Theta= 0
UNET Theta Warmup= 0
UNET ZTol= 0
UNET ZSATol= 0
UNET MxIter= 0
UNET MaxInSteps= 0
UNET DtIC= 0
UNET DtMin= 0
UNET MaxCRTS= 0
UNET WFStab= 0
UNET SFStab= 0
UNET WFX= 1
UNET SFX= 1
UNET DSS MLevel= 1
UNET DZMax Abort= 0
UNET Convert EG Bridges= 0
UNET Use Existing IB Tables= 0
UNET Froude Reduction=False
UNET Froude Limit= 0
UNET Froude Power= 0
UNET Time Slicing=0,0, 5
Write IC File= 0
Echo Input=False
Echo Output=False
Write Detailed= 0
Detailed Automatic Start=False, 0
WQ ULTIMATE=-1
WQ Max Comp Step=1HOUR
WQ Output Interval=15MIN
WQ Output Selected Increments= 0
WQ Output face flow=0
WQ Output face velocity=0
WQ Output face area=0
WQ Output face dispersion=0
WQ Output cell volume=0
WQ Output cell surface area=0
WQ Output cell continuity=0
WQ Output face conc=0
WQ Output face dconc_dx=0
WQ Output face courant=0
WQ Output face peclet=0
WQ Output face adv mass=0
WQ Output face disp mass=0
WQ Output cell mass=0
WQ Output cell source sink temp=0
WQ Output cell source sink nsm=0
WQ Output MaxMinRange=-1
WQ Daily Max Min Mean=-1
WQ Daily Range=0
WQ Daily Time=0
WQ Create Restart=0
WQ Fixed Restart=0
WQ System Summary=False
Sorting and Armoring Iterations= 10
XS Update Threshold= 0.02
Hydraulics Update Threshold= 0.02
Energy Slope Method= 1
Volume Change Method= 0
XS Weighting Method= 0
Number of US Weighted Cross Sections= 1
Number of DS Weighted Cross Sections= 1
Upstream XS Weight=0.25
Main XS Weight=0.5
Downstream XS Weight=0.25
Number of DS XS's Weighted with US Boundary= 1
Upstream Boundary Weight= 1
Weight of XSs Associated with US Boundary= 0
Number of US XS's Weighted with DS Boundary= 1
Downstream Boundary Weight= 0.5
Weight of XSs Associated with DS Boundary= 0.5
Sediment Output Level= 4
Mass or Volume Output= 0
Output Increment Type= 1
Profile and TS Output Increment= 10
XS Output Flag= 0
XS Output Increment= 10
Disregard all LS=0
Disregard all Conn=0
Disregard all Breaches=0
Disregard all Pumps=0

--- np13.f01 (steady flow) ---

Flow Title=USGS Regression Equation
Program Version=4.00
Number of Profiles= 1
Profile Names=P100yr
River Rch & RM=np13,Main            ,6693.2
     355
River Rch & RM=np13,Main            ,6237.6
     355
River Rch & RM=np13,Main            ,5967.7
     440
River Rch & RM=np13,Main            ,3828.4
     489
River Rch & RM=np13,Main            ,3639.4
     606
River Rch & RM=np13,Main            ,551.2
     661
Boundary for River Rch & Prof#=np13,Main            , 1
Up Type= 0
Dn Type= 3
Dn Slope=0.013867
DSS Import GetInterval= 0
DSS Import GetPeak= 0
DSS Import FillOption= 0

--- np13.g01 (geometry) ---

Geom Title=USGS 3m DEM
Program Version=4.00

River Reach=np13            ,Main
Reach XY= 30
     1613070.733       288879.61     1612878.901      288667.268
     1612815.177      288667.268     1612666.968      288577.503
     1612409.033      288484.697     1612281.025      288494.084
     1612087.358      288613.686      1611902.11      288478.434
     1611767.913      288512.991     1611592.566      288450.491
     1611123.816      288387.991     1610838.978      288520.812
     1610188.052      288252.574     1610098.587      288239.714
     1609917.219      288280.352     1609639.441      288162.297
     1609444.997       288026.88     1609379.025      287898.408
     1609302.636      287846.325     1608880.761      287795.977
      1608685.57      287818.905      1608332.15       287558.13
     1608080.414      287539.033     1607908.539      287490.422
     1607710.622      287381.047     1607625.552      287403.616
     1607498.816      287358.477     1607387.481      287257.874
     1607185.004      287184.787     1607097.822      287189.964

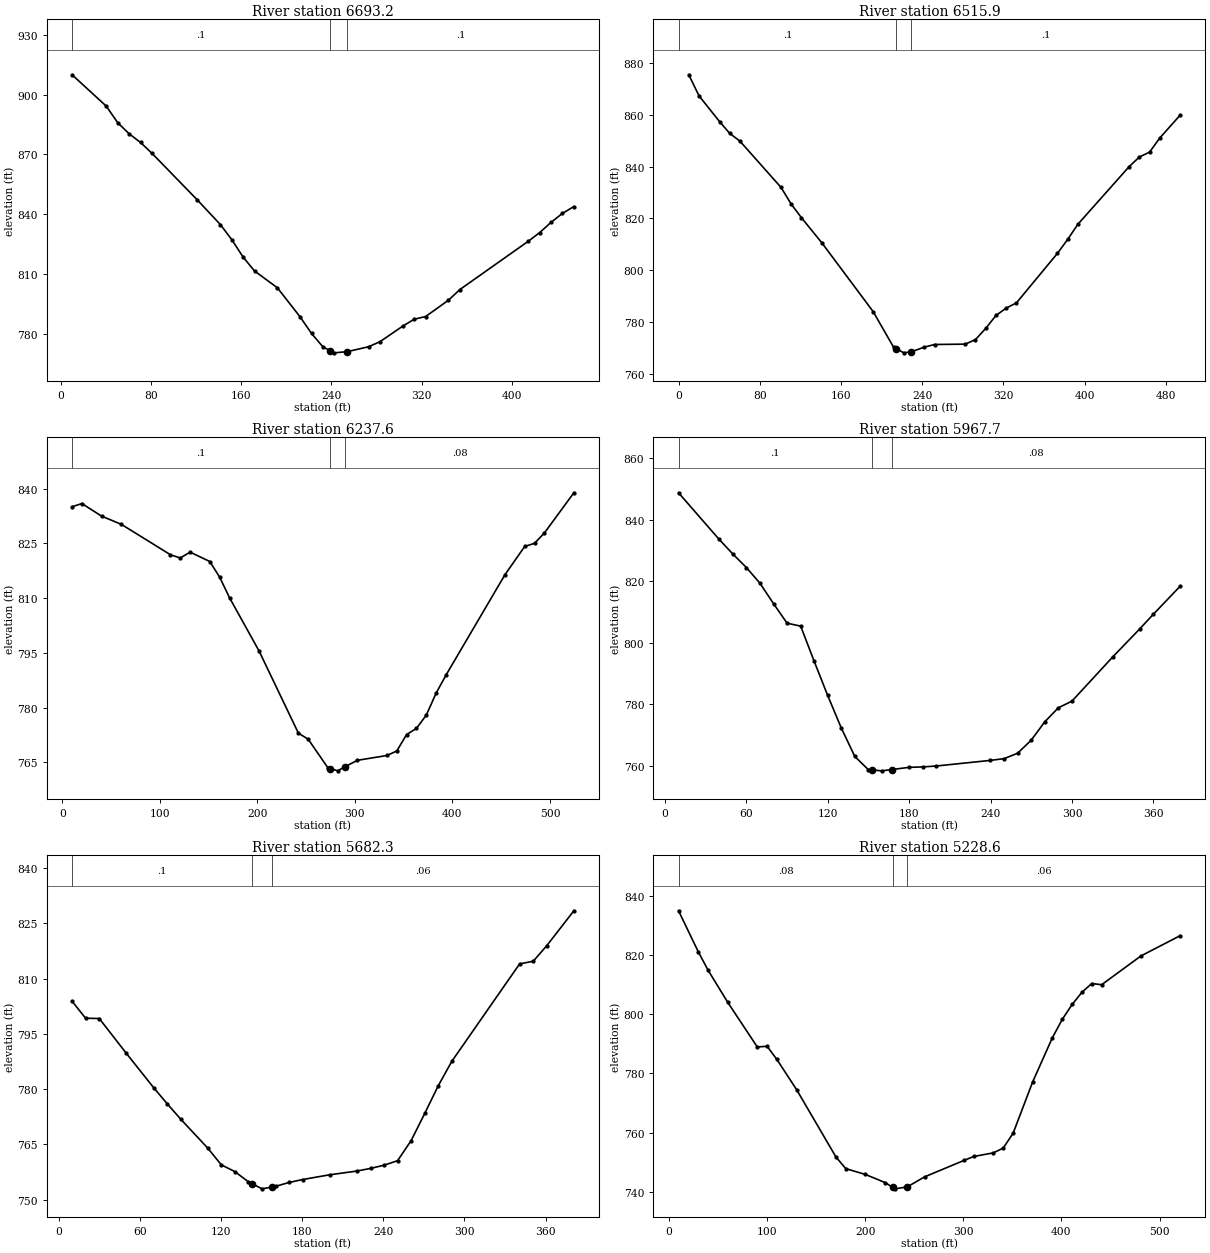
Type RM Length L Ch R = 1 ,6693.2  ,175.5,177.3,179.1
XS GIS Cut Line= 2
     1613224.449      288692.963     1612916.388      289027.811
#Sta/Elev= 30
    10.1  909.88    40.4   894.2    50.6  885.87    60.7  880.37    70.8  876.01
    80.9  870.62   121.3  847.17   141.6  834.93   151.7  827.38   161.8  818.62
   171.9  811.69   192.1  803.33   212.3  788.73   222.4  780.46   232.6  773.68
   239.2 771.763   242.7  770.75   254.2 771.359     273   773.8   283.1  776.33
   303.3  784.11   313.4  787.56   323.6  788.93   343.8  797.08   353.9   802.4
   414.6  826.59   424.7  830.91   434.8  836.05   444.9  840.53     455  843.94
#Mann= 3 , 0 , 0
    10.1      .1       0   239.2    .045       0   254.2      .1       0
Bank Sta=239.2,254.2
XS Rating Curve= 0 ,0
Exp/Cntr=0.3,0.1

Type RM Length L Ch R = 1 ,6515.9  ,283.6,278.3,273.1
XS GIS Cut Line= 2
     1613108.943      288586.634     1612746.176      288922.375
#Sta/Elev= 30
    10.1  875.49    20.2  867.34    40.4  857.42    50.4  852.87    60.5  849.84
   100.9  832.02     111  825.53   121.1  820.27   141.2  810.57   191.7  784.03
   211.8  770.29   214.4  769.72   221.9  768.09   229.4   768.5   242.1   770.3
   252.2  771.31   282.5  771.45   292.5  773.21   302.6  777.52   312.7  782.53
   322.8  785.38   332.9   787.4   373.2  806.49   383.3  811.89   393.4  817.76
   443.9  840.03   453.9  843.71     464  845.62   474.1  851.09   494.3  859.97
#Mann= 3 , 0 , 0
       0      .1       0   214.4    .045       0   229.4      .1       0
Bank Sta=214.4,229.4
XS Rating Curve= 0 ,0
Exp/Cntr=0.3,0.1

Type RM Length L Ch R = 1 ,6237.6  ,278.4,269.9,261.4
XS GIS Cut Line= 2
      1612882.69      288380.477     1612578.528      288807.795
#Sta/Elev= 30
    10.1  835.08    20.2  835.96    40.3  832.51    60.5  830.27     111  821.91
     121  821.02   131.1  822.63   151.3  820.06   161.4  815.76   171.5  810.13
   201.7  795.56   242.1  772.99   252.2   771.3   272.3   763.5   274.9  763.28
   282.4  762.64   289.9  763.77   302.6  765.53   332.9  766.85     343  768.09
     353  772.59   363.1  774.27   373.2  777.91   383.3  783.95   393.4  788.89
   453.9  816.45   474.1  824.18   484.2  825.05   494.3  827.89   524.5  838.91
#Mann= 3 , 0 , 0
    10.1      .1       0   274.9    .045       0   289.9     .08       0
Bank Sta=274.9,289.9
XS Rating Curve= 0 ,0
Exp/Cntr=0.3,0.1

Type RM Length L Ch R = 1 ,5967.7  ,295.9,285.3,274.8
XS GIS Cut Line= 2
     1612508.489      288361.074     1612417.018      288729.731
#Sta/Elev= 30
      10  848.72      40  833.54      50  828.83      60  824.43      70  819.32
      80  812.69      90  806.33     100  805.39     110  793.91   119.9  782.86
   129.9  772.32   139.9  763.02   149.9  758.73   152.4  758.64   159.9  758.35
   167.4  758.78   179.9  759.49   189.9  759.62   199.9  759.92   239.9  761.75
   249.9  762.31   259.9  764.07   269.9  768.32   279.9  774.28   289.9  778.85
   299.9  780.99   329.9  795.33   349.8  804.44   359.8  809.18   379.8  818.41
#Mann= 3 , 0 , 0
      10      .1       0   152.4    .045       0   167.4     .08       0
Bank Sta=152.4,167.4
XS Rating Curve= 0 ,0
Exp/Cntr=0.3,0.1

Type RM Length L Ch R = 1 ,5682.3  ,454.4,453.7,452.9
XS GIS Cut Line= 2
     1612168.937      288387.406     1612253.478      288758.835
#Sta/Elev= 30
      10  803.87      20  799.25    30.1  799.17    50.1  789.72    70.2  780.43
    80.2  776.06    90.2  771.87   110.3  763.96   120.3  759.42   130.3  757.59
   140.3  754.82   142.9  754.33   150.4   752.9   157.9   753.4   160.4  753.57
   170.4  754.63   180.4  755.43   200.5  756.72   220.5  757.73   230.6  758.45
   240.6  759.32   250.6  760.55   260.6  765.99   270.7   773.4   280.7  780.93
   290.7  787.55   340.8  814.01   350.9  814.74   360.9  818.97   380.9  828.44
#Mann= 3 , 0 , 0
      10      .1       0   142.9    .045       0   157.9     .06       0
Bank Sta=142.9,157.9
XS Rating Curve= 0 ,0
Exp/Cntr=0.3,0.1

Type RM Length L Ch R = 1 ,5228.6  ,240.4,253,265.6
XS GIS Cut Line= 2
     1611760.773      288269.463     1611915.312      288767.151
#Sta/Elev= 30
      10  835.07    30.1   821.2    40.1  814.95    60.1  804.09    90.2  788.98
   100.2  789.21   110.2  784.74   130.3  774.51   170.4   751.7   180.4  747.79
   200.4  745.82   220.5  743.07     228 741.487   230.5  740.96     243 741.628
   260.6  745.01   300.7  750.57   310.7  751.91   330.7  753.14   340.7  754.76
   350.8  759.79   370.8  777.24   390.8  792.12   400.9  798.35   410.9  803.36
   420.9  807.49   430.9  810.44     441  810.05     481  819.79   521.1  826.67
#Mann= 3 , 0 , 0
      10     .08       0     228    .045       0     243     .06       0
Bank Sta=228,243
XS Rating Curve= 0 ,0
Exp/Cntr=0.3,0.1

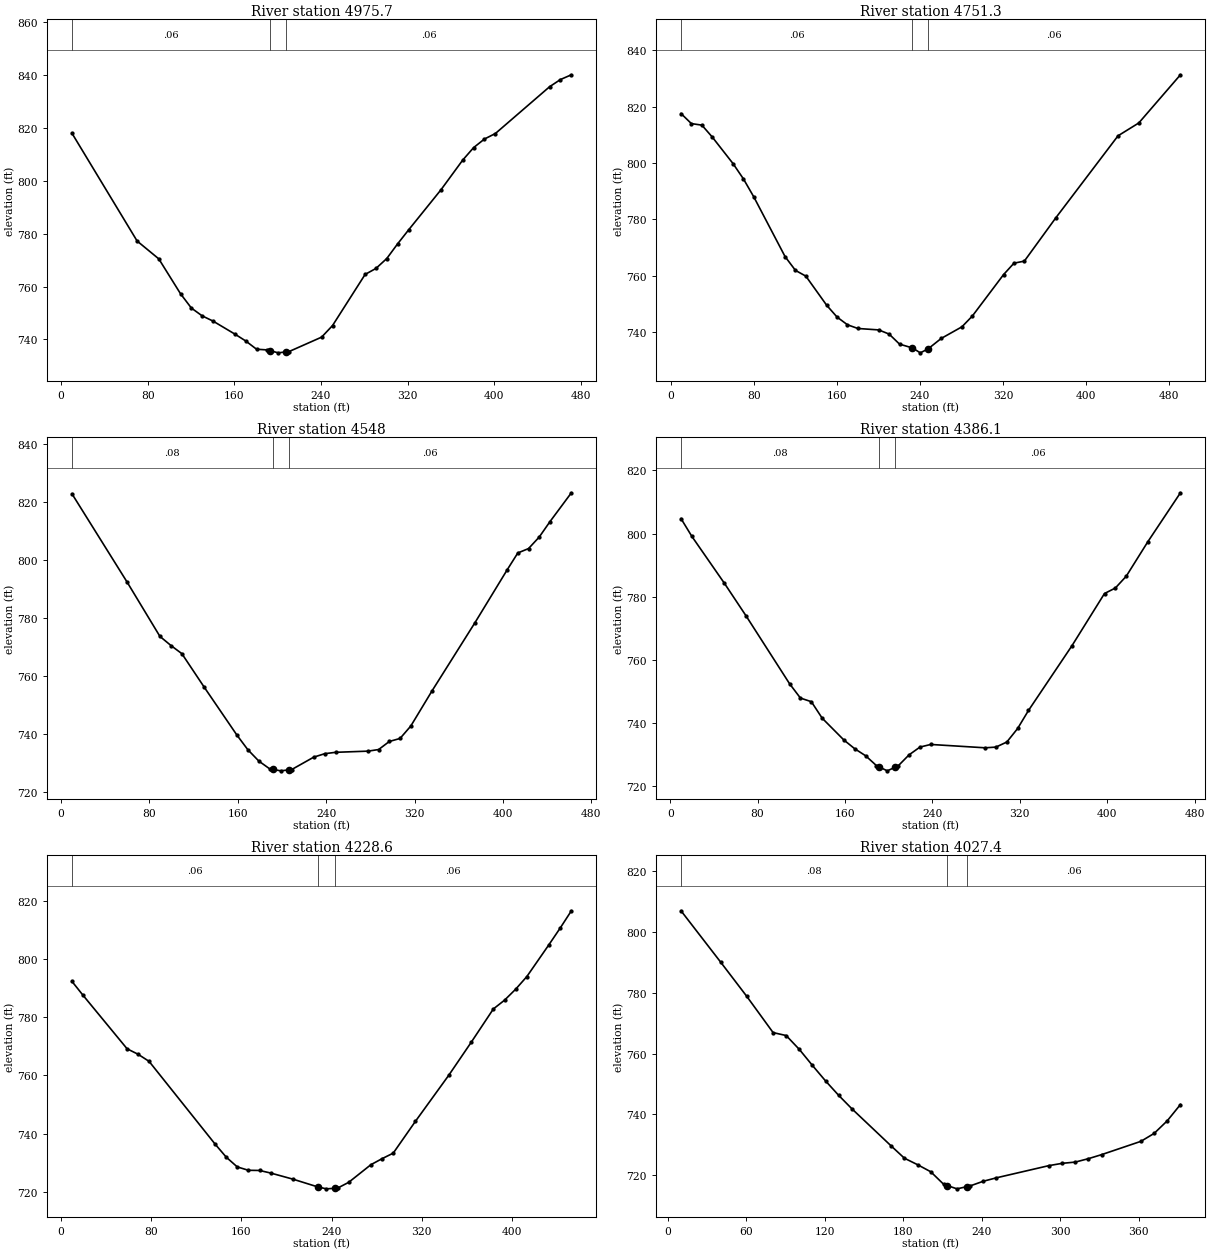
Type RM Length L Ch R = 1 ,4975.7  ,222.6,224.4,226.2
XS GIS Cut Line= 2
     1611639.512      288262.673     1611525.865      288720.029
#Sta/Elev= 30
      10  818.01    70.2  777.23    90.2  770.49   110.3  757.28   120.3  751.88
   130.3  748.92   140.4  746.93   160.4  742.05   170.5  739.43   180.5  736.31
   190.5  736.04     193  735.77   200.5  734.94     208  735.31   210.6  735.44
   240.6  740.88   250.7  745.27   280.8  764.61   290.8  766.87   300.8  770.62
   310.8  776.17   320.9  781.42   350.9  796.65     371  807.89     381  812.57
     391  815.82   401.1   817.9   451.2  835.61   461.2  838.32   471.3  840.12
#Mann= 3 , 0 , 0
      10     .06       0     193    .045       0     208     .06       0
Bank Sta=193,208
XS Rating Curve= 0 ,0
Exp/Cntr=0.3,0.1

Type RM Length L Ch R = 1 ,4751.3  ,208.9,203.3,197.7
XS GIS Cut Line= 2
     1611445.482      288196.148     1611290.258       288661.82
#Sta/Elev= 30
      10  817.53      20  813.95    30.1  813.41    40.1  809.18    60.1  799.75
    70.1  794.32    80.1  787.92   110.2  766.73   120.2  761.83   130.2  759.79
   150.3  749.43   160.3  745.24   170.3  742.51   180.3   741.2   200.4  740.69
   210.4  739.21   220.4  735.65   232.9  734.28   240.4  732.55   247.9  733.95
   260.5  737.65   280.5  741.79   290.5  745.61   320.6  760.34   330.6  764.39
   340.6  765.12   370.7   780.4   430.8  809.62   450.8  814.18   490.9  831.29
#Mann= 3 , 0 , 0
      10     .06       0   232.9    .045       0   247.9     .06       0
Bank Sta=232.9,247.9
XS Rating Curve= 0 ,0
Exp/Cntr=0.3,0.1

Type RM Length L Ch R = 1 ,4548    ,177.1,161.9,146.8
XS GIS Cut Line= 3
     1611184.927      288190.604      1611166.91      288438.686
     1611225.119      288643.803
#Sta/Elev= 30
     9.9  822.73    59.7  792.41    89.5  773.65    99.5   770.5   109.4  767.69
   129.3  756.34   159.2  739.67   169.1  734.63   179.1   730.7     189  728.01
   191.5  727.85     199  727.35   206.5   727.7   208.9  727.81   228.8  732.07
   238.8  733.26   248.7  733.73   277.8  734.13   287.5  734.68   297.2  737.46
   306.9   738.5   316.6  742.76     336  754.97   374.7  778.35   403.8  796.51
   413.5  802.36   423.2  803.87   432.9  807.85   442.6  813.14     462  823.08
#Mann= 3 , 0 , 0
     9.9     .08       0   191.5    .045       0   206.5     .06       0
Bank Sta=191.5,206.5
XS Rating Curve= 0 ,0
Exp/Cntr=0.3,0.1

Type RM Length L Ch R = 1 ,4386.1  ,150,157.5,165
XS GIS Cut Line= 2
     1610904.969      288258.515      1611166.91      288645.189
#Sta/Elev= 30
     9.9  804.75    19.9  799.08    49.7  784.21    69.6  773.84   109.3   752.4
   119.2  747.88   129.2  746.73   139.1  741.51     159  734.58   168.9  731.82
   178.9  729.59   188.8  726.47   191.2  726.07   198.7  724.82   206.2  726.01
   208.7  726.41   218.6  729.88   228.6  732.35   238.5  733.18   288.2  732.12
   298.1  732.34   308.1  733.95     318  738.24   327.9  743.94   367.7  764.46
   397.5  781.01   407.4  782.74   417.4  786.49   437.2  797.44     467  812.93
#Mann= 3 , 0 , 0
     9.9     .08       0   191.2    .045       0   206.2     .06       0
Bank Sta=191.2,206.2
XS Rating Curve= 0 ,0
Exp/Cntr=0.3,0.1

Type RM Length L Ch R = 1 ,4228.6  ,184.1,201.1,218.2
XS GIS Cut Line= 3
     1610885.566      288283.462     1610866.163      288438.686
     1610945.161      288724.187
#Sta/Elev= 30
     9.8  792.28    19.6  787.52    58.7  769.13    68.4  767.26    78.2  764.81
   136.9  736.32   146.7  731.88   156.4  728.56   166.3   727.4   176.2  727.34
   186.1  726.45   205.8  724.35   227.9  721.68   235.4  721.03   242.9  721.21
   245.3  721.27   255.2  723.26   274.9  729.32   284.8  731.39   294.7  733.29
   314.4  744.22     344  760.06   363.8  771.33   383.5  782.81   393.4  785.82
   403.3   789.6   413.2  793.94   432.9  804.94   442.8  810.61   452.7  816.53
#Mann= 3 , 0 , 0
     9.8     .06       0   227.9    .045       0   242.9     .06       0
Bank Sta=227.9,242.9
XS Rating Curve= 0 ,0
Exp/Cntr=0.3,0.1

Type RM Length L Ch R = 1 ,4027.4  ,199.7,199.1,198.5
XS GIS Cut Line= 2
     1610803.797      288264.059     1610623.626      288611.927
#Sta/Elev= 30
      10  807.04    40.2  790.19    60.3  778.84    80.4  766.92    90.4  765.95
   100.5  761.36   110.5  756.09   120.5     751   130.6  746.22   140.6  741.84
   170.8  729.53   180.8  725.54   190.9   723.4   200.9  721.09   210.9  716.91
   213.5  716.54     221  715.46   228.5  716.18     231  716.42   241.1  717.96
   251.1  719.09   291.3  723.11   301.4  723.86   311.4  724.27   321.4  725.39
   331.5  726.72   361.6  731.11   371.7  733.72   381.7  737.86   391.8  743.23
#Mann= 3 , 0 , 0
      10     .08       0   213.5    .045       0   228.5     .06       0
Bank Sta=213.5,228.5
XS Rating Curve= 0 ,0
Exp/Cntr=0.3,0.1

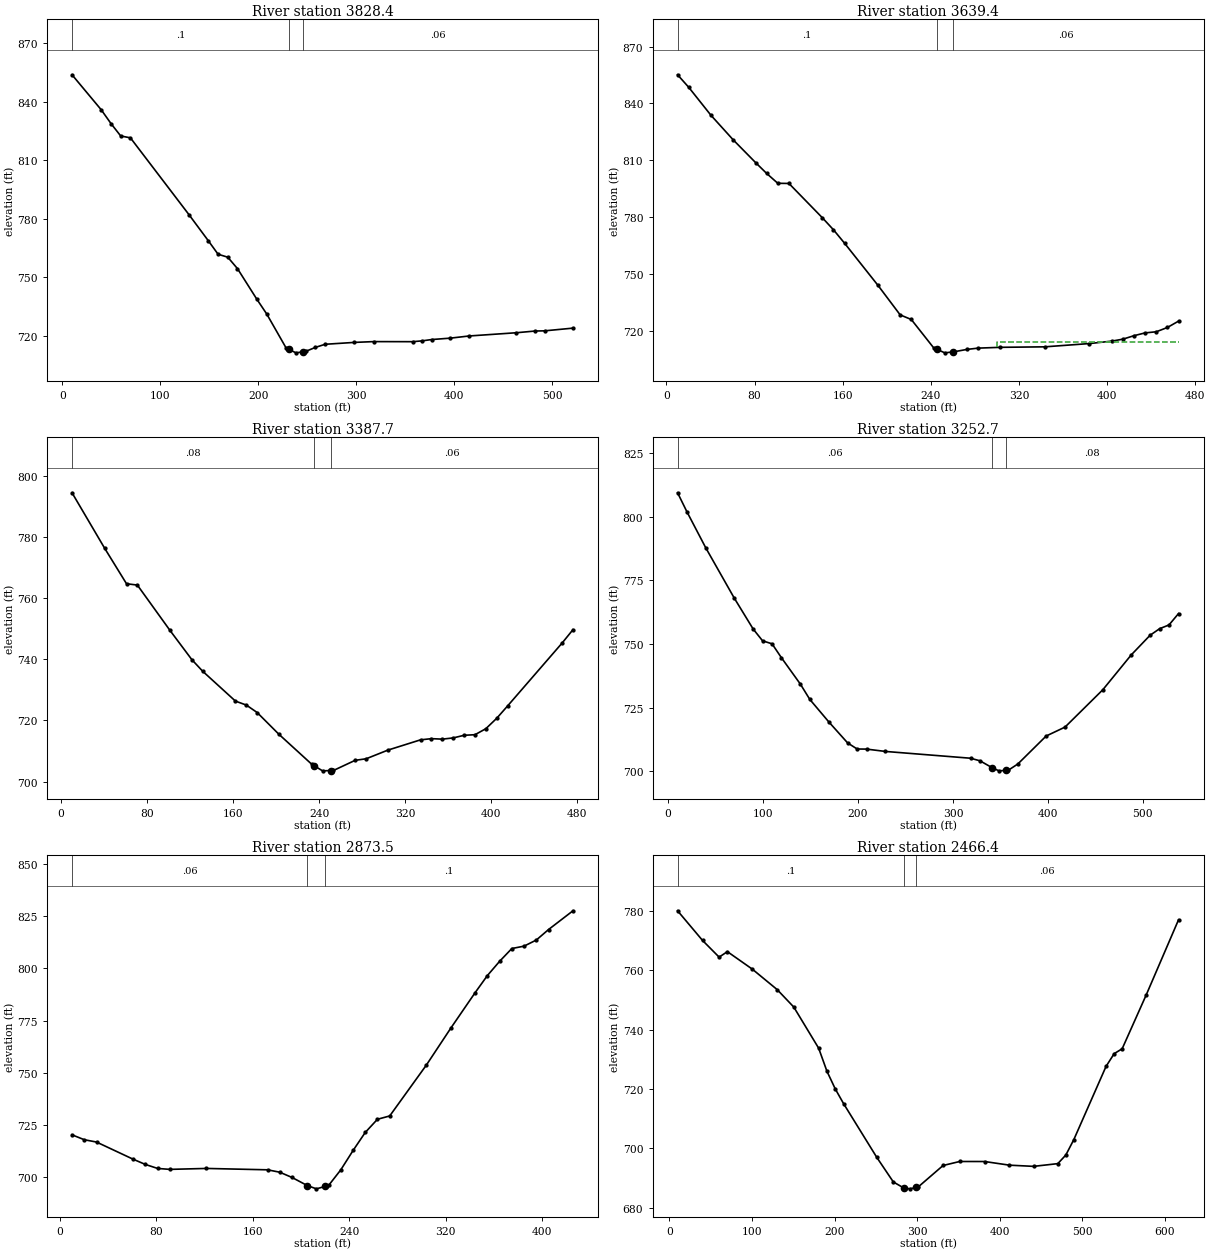
Type RM Length L Ch R = 1 ,3828.4  ,188.5,189,189.6
XS GIS Cut Line= 3
     1610627.783        288161.5     1610471.765      288483.365
     1610483.647      288646.575
#Sta/Elev= 30
     9.9  853.77    39.7  835.83    49.7  828.74    59.6  822.39    69.5  821.44
   129.2   782.1     149  768.69     159  761.75   168.9  760.23   178.8  754.37
   198.7  738.58   208.6  731.16   228.5  713.64     231  713.03   238.5  711.19
     246  711.73   248.4  711.91   258.3  713.98   268.3  715.58   298.1  716.54
   317.9  716.95   357.7  716.91   367.3  717.33   376.9     718   396.2  718.73
   415.4  719.84   463.6   721.5   482.8  722.38   492.4  722.47   521.3  723.86
#Mann= 3 , 0 , 0
     9.9      .1       0     231    .045       0     246     .06       0
Bank Sta=231,246
XS Rating Curve= 0 ,0
Exp/Cntr=0.3,0.1

Type RM Length L Ch R = 1 ,3639.4  ,257,251.7,247
XS GIS Cut Line= 2
     1610457.314      288094.975     1610243.881      288507.982
#Sta/Elev= 30
    10.1  855.11    20.2  848.52    40.4  833.74    60.6  820.77    80.9  808.79
      91  803.03   101.1  797.83   111.2  797.75   141.5  779.67   151.6  773.32
   161.7  766.21     192  743.99   212.2  728.37   222.3  725.94   242.6  710.98
   245.2   710.3   252.7  708.34   260.2  708.82   272.9  710.15     283  710.83
   303.2  711.25   343.6  711.51     384  713.24   404.3  714.52   414.4  715.56
   424.5   717.4   434.6  718.87   444.7  719.46   454.8  721.73   464.9  725.07
#Mann= 3 , 0 , 0
    10.1      .1       0   245.2    .045       0   260.2     .06       0
#XS Ineff= 2 , 0
       0                     300       0     714
Permanent Ineff=
       F       F
Bank Sta=245.2,260.2
XS Rating Curve= 0 ,0
Exp/Cntr=0.3,0.1

Type RM Length L Ch R = 1 ,3387.7  ,139.2,135,130
XS GIS Cut Line= 2
     1610164.883      287992.416     1610052.623      288455.317
#Sta/Elev= 30
    10.1  794.39    40.5  776.23    60.8  764.66    70.9  764.22   101.3  749.38
   121.6  739.85   131.7  736.05   162.2  726.29   172.3     725   182.4  722.56
   202.7  715.43   233.1  705.68   235.7  705.12   243.2   703.5   250.7  703.59
   253.4  703.62   273.6  706.94   283.8  707.44     304  710.27   334.4  713.63
   344.6  714.02   354.7  713.86   364.8  714.26     375  715.12   385.1  715.31
   395.2  717.27   405.4   720.7   415.5  724.73   466.2  745.28   476.3  749.65
#Mann= 3 , 0 , 0
    10.1     .08       0   235.7    .045       0   250.7     .06       0
Bank Sta=235.7,250.7
XS Rating Curve= 0 ,0
Exp/Cntr=0.3,0.1

Type RM Length L Ch R = 1 ,3252.7  ,365.7,379.2,392.8
XS GIS Cut Line= 2
     1609999.958      287934.208     1609965.309      288470.562
#Sta/Elev= 30
      10  809.46    19.9  801.95    39.8  787.73    69.7  768.03    89.6  755.87
    99.5  751.24   109.5  750.05   119.4  744.56   139.3  734.21   149.3  728.16
   169.2  719.36   189.1  711.06   199.1  708.68     209  708.64   228.9  707.72
   318.5  705.05   328.5  704.03   340.9  701.39   348.4  700.09   355.9  700.28
   358.3  700.34   368.3  702.78   398.1  713.78     418   717.3   457.8  731.99
   487.7  745.68   507.6  753.43   517.6     756   527.5  757.48   537.5  761.95
#Mann= 3 , 0 , 0
      10     .06       0   340.9    .045       0   355.9     .08       0
Bank Sta=340.9,355.9
XS Rating Curve= 0 ,0
Exp/Cntr=0.3,0.1

Type RM Length L Ch R = 1 ,2873.5  ,396.2,407.1,420.1
XS GIS Cut Line= 2
     1609754.648      287988.259     1609492.708      288323.654
#Sta/Elev= 30
    10.1  720.26    20.3  717.91    30.4   716.8    60.8  708.57    70.9  706.07
    81.1  704.15    91.2   703.7   121.6  704.15   172.3  703.49   182.4  702.34
   192.5  699.84   205.3  695.93   212.8  694.37   220.3  695.57   222.9  695.99
     233  703.46   243.2  712.75   253.3   721.4   263.4  727.71   273.6  729.31
     304   753.7   324.2  771.35   344.5  788.46   354.6   796.6   364.8  803.47
   374.9  809.57     385   810.7   395.2  813.64   405.3  818.65   425.6  827.66
#Mann= 3 , 0 , 0
    10.1     .06       0   205.3    .045       0   220.3      .1       0
Bank Sta=205.3,220.3
XS Rating Curve= 0 ,0
Exp/Cntr=0.3,0.1

Type RM Length L Ch R = 1 ,2466.4  ,352.2,327.2,300.2
XS GIS Cut Line= 3
     1609611.897      287752.651     1609237.697      287924.506
     1609172.558      288118.536
#Sta/Elev= 30
      10  780.02    40.2  770.04    60.3  764.41    70.3  766.26   100.4  760.38
   130.6  753.47   150.7  747.59   180.8  733.74   190.8  725.99   200.9  720.02
   210.9   715.1   251.1     697   271.2  688.69   283.8  686.68   291.3  686.38
   298.8  686.86   301.3  687.02   331.4  694.24   351.5  695.59   381.6  695.58
   411.8  694.35     441  693.95   470.3  694.87     480  697.77   489.7  702.98
   528.7  727.63   538.5   731.9   548.2  733.56   577.5  751.81   616.4  776.97
#Mann= 3 , 0 , 0
      10      .1       0   283.8    .045       0   298.8     .06       0
Bank Sta=283.8,298.8
XS Rating Curve= 0 ,0
Exp/Cntr=0.3,0.1

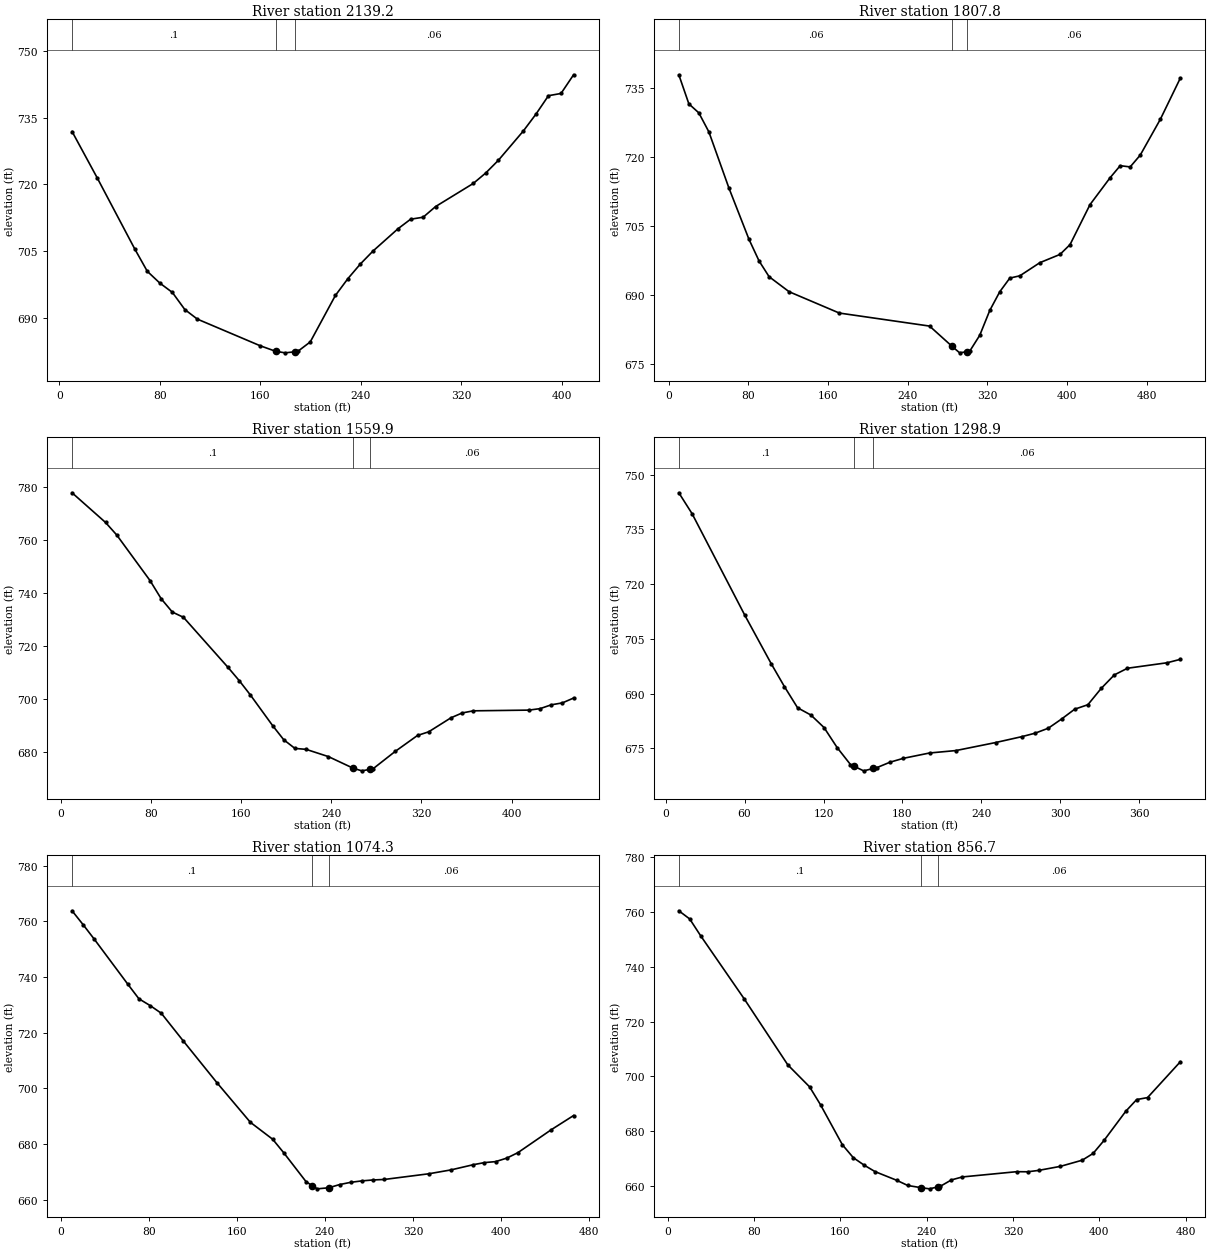
Type RM Length L Ch R = 1 ,2139.2  ,323,331.4,339.8
XS GIS Cut Line= 2
     1609043.667      287632.075     1609022.878      288040.924
#Sta/Elev= 30
      10  731.88      30   721.5    59.9  705.56    69.9  700.54    79.9  697.89
    89.9  695.79    99.8  691.96   109.8  689.81   159.8  683.84   172.2  682.59
   179.7  682.25   187.2  682.48   189.7  682.56   199.7   684.7   219.7  695.11
   229.7   698.9   239.6  702.17   249.6  705.06   269.6  710.08   279.6  712.21
   289.6  712.66   299.5  715.05   329.5  720.23   339.5  722.59   349.5  725.42
   369.4     732   379.4  735.76   389.4  739.91   399.4  740.41   409.4   744.6
#Mann= 3 , 0 , 0
      10      .1       0   172.2    .045       0   187.2     .06       0
Bank Sta=172.2,187.2
XS Rating Curve= 0 ,0
Exp/Cntr=0.3,0.1

Type RM Length L Ch R = 1 ,1807.8  ,243.7,247.8,252
XS GIS Cut Line= 2
      1608824.69      287554.463     1608619.572      288025.679
#Sta/Elev= 30
    10.1   737.9    20.2  731.58    30.2  729.63    40.3   725.5    60.5  713.27
    80.6  702.16    90.7  697.48   100.8  694.05   120.9  690.79   171.3  686.16
     262  683.33   284.7  678.91   292.2  677.52   299.7  677.78   302.3  677.87
   312.4  681.33   322.5  686.74   332.5  690.78   342.6  693.75   352.7  694.25
   372.8   697.1     393  698.89   403.1  701.02   423.2  709.72   443.4  715.56
   453.5  718.16   463.5  717.89   473.6  720.45   493.8  728.23   513.9  737.18
#Mann= 3 , 0 , 0
    10.1     .06       0   284.7    .045       0   299.7     .06       0
Bank Sta=284.7,299.7
XS Rating Curve= 0 ,0
Exp/Cntr=0.3,0.1

Type RM Length L Ch R = 1 ,1559.9  ,271.8,261.1,250.3
XS GIS Cut Line= 3
     1608644.699      287476.314      1608518.26      287665.443
     1608392.066      287854.734
#Sta/Elev= 30
     9.9  777.75    39.6  766.55    49.5  761.83    79.1  744.59      89  737.72
    98.9  732.69   108.8   730.7   148.4  711.75   158.3  706.77   168.2  701.35
   187.9   689.8   197.8  684.44   207.7  681.18   217.6  680.83   237.4  678.09
   259.6  673.66   267.1  672.71   274.6  673.29     277  673.48   296.7  680.05
   316.5  686.08   326.4  687.45   346.2  692.75   356.1  694.57     366  695.38
   415.4  695.65   425.3  696.21   435.2  697.65   445.1  698.38     455  700.21
#Mann= 3 , 0 , 0
     9.9      .1       0   259.6    .045       0   274.6     .06       0
Bank Sta=259.6,274.6
XS Rating Curve= 0 ,0
Exp/Cntr=0.3,0.1

Type RM Length L Ch R = 1 ,1298.9  ,224.9,224.5,224.2
XS GIS Cut Line= 2
     1608306.352      287411.712     1608256.459      287799.772
#Sta/Elev= 30
      10  745.05    20.1  739.31    60.2  711.47    80.3  698.17    90.3  691.92
   100.3  686.12   110.4  684.14   120.4  680.71   130.4   675.2   140.5  670.57
     143  670.14   150.5  668.84     158  669.49   160.5  669.71   170.5   671.2
   180.6  672.26   200.6  673.73   220.7   674.4   250.8  676.59   270.9  678.22
   280.9  679.16   290.9  680.52     301  683.04     311  685.74     321  686.96
   331.1  691.42   341.1  695.13   351.1  696.96   381.2  698.46   391.3   699.4
#Mann= 3 , 0 , 0
      10      .1       0     143    .045       0     158     .06       0
Bank Sta=143,158
XS Rating Curve= 0 ,0
Exp/Cntr=0.3,0.1

Type RM Length L Ch R = 1 ,1074.3  ,211.2,217.7,224.1
XS GIS Cut Line= 2
     1608091.533      287307.767     1608037.482      287770.668
#Sta/Elev= 30
    10.1  763.79    20.3  758.73    30.4  753.54    60.8  737.43    70.9  732.19
    81.1  729.76    91.2  727.02   111.4  716.97   141.8  702.08   172.2  687.86
   192.5  681.77   202.6  676.89   222.9  666.51   228.5 665.108     233  663.98
   243.5 664.365   253.3  665.51   263.4  666.32   273.5  666.83   283.7  667.17
   293.8  667.34   334.3  669.38   354.6  670.78   374.9  672.65     385   673.4
   395.1  673.75   405.3  675.01   415.4  676.97   445.8  685.22     466  690.29
#Mann= 3 , 0 , 0
    10.1      .1       0   228.5    .045       0   243.5     .06       0
Bank Sta=228.5,243.5
XS Rating Curve= 0 ,0
Exp/Cntr=0.3,0.1

Type RM Length L Ch R = 1 ,856.7   ,310.6,305.4,298.8
XS GIS Cut Line= 2
     1607947.397      287256.488     1607763.068      287694.442
#Sta/Elev= 30
    10.1  760.34    20.2  757.36    30.3  751.27    70.8  728.23   111.2  704.21
   131.4  696.21   141.5   689.7   161.8  675.12   171.9  670.43     182   667.7
   192.1  665.35   212.3  662.17   222.4   660.3   235.1  659.48   242.6  659.08
   250.1  659.78   252.7  660.03   262.9  662.33     273  663.41   323.5  665.33
   333.6  665.29   343.7  665.79     364  667.27   384.2  669.51   394.3  671.97
   404.4  676.69   424.6  687.33   434.7  691.59   444.8  692.31   475.2  705.36
#Mann= 3 , 0 , 0
    10.1      .1       0   235.1    .045       0   250.1     .06       0
Bank Sta=235.1,250.1
XS Rating Curve= 0 ,0
Exp/Cntr=0.3,0.1

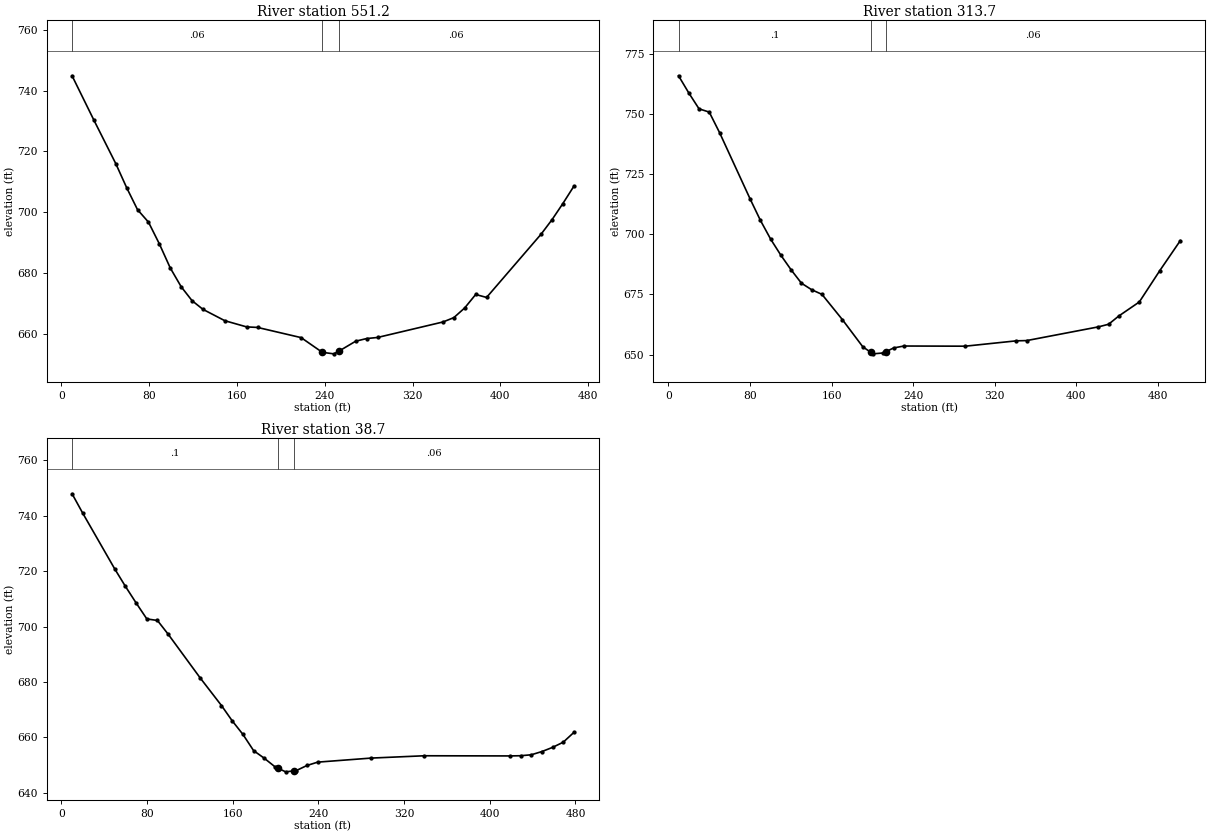
Type RM Length L Ch R = 1 ,551.2   ,235.4,237.6,239.8
XS GIS Cut Line= 2
     1607643.783      287157.743     1607536.234      287612.043
#Sta/Elev= 30
     9.9  744.87    29.8  730.28    49.7  716.01    59.6  708.11    69.5  700.88
    79.5  696.77    89.4  689.63    99.3  681.74   109.3  675.53   119.2  670.96
   129.1  668.12     149  664.39   168.9  662.35   178.8  662.18   218.5  658.83
   237.8 653.996   248.3   653.5   252.8 654.358   268.2  657.65   278.1  658.52
   288.1  658.88   347.7  663.97   357.6   665.4   367.5  668.59   377.5  673.01
   387.4  672.03   437.1  692.84     447  697.58   456.9  702.89   466.9  708.57
#Mann= 3 , 0 , 0
     9.9     .06       0   237.8    .045       0   252.8     .06       0
Bank Sta=237.8,252.8
XS Rating Curve= 0 ,0
Exp/Cntr=0.3,0.1

Type RM Length L Ch R = 1 ,313.7   ,281.6,275,268.4
XS GIS Cut Line= 2
     1607460.936       287072.16      1607296.01      287546.147
#Sta/Elev= 30
      10  765.88    20.1  758.71    30.1  752.14    40.1  750.79    50.2  742.28
    80.3  714.58    90.3  705.76   100.4  697.92   110.4  691.25   120.4  685.21
   130.5  679.67   140.5  676.97   150.6  675.04   170.6  664.55   190.7  653.21
   198.2 651.043   200.7  650.32   210.8  650.69   213.2 651.187   220.8  652.76
   230.9  653.57   291.1   653.5   341.3  655.73   351.3  655.83   421.6  661.53
   431.6  662.62   441.6  666.05   461.7  671.88   481.8  684.92   501.9  697.38
#Mann= 3 , 0 , 0
      10      .1       0   198.2    .045       0   213.2     .06       0
Bank Sta=198.2,213.2
XS Rating Curve= 0 ,0
Exp/Cntr=0.3,0.1

Type RM Length L Ch R = 1 ,38.7    ,40.9,38.7,36.4
XS GIS Cut Line= 2
     1607144.944      286977.917     1607125.541      287456.062
#Sta/Elev= 30
      10  747.91    19.9  740.95    49.8  720.82    59.8  714.51    69.8  708.53
    79.8  702.76    89.7   702.2    99.7  697.26   129.6  681.48   149.5  671.51
   159.5     666   169.5  661.11   179.5  655.24   189.4  652.51   199.4  649.43
   201.9  648.97   209.4  647.59   216.9  647.93   219.3  648.04   229.3  649.88
   239.3  651.09   289.1  652.55     339  653.39   418.7  653.33   428.7   653.4
   438.7  653.74   448.6   654.9   458.6  656.41   468.6  658.29   478.5  661.81
#Mann= 3 , 0 , 0
      10      .1       0   201.9    .045       0   216.9     .06       0
Bank Sta=201.9,216.9
XS Rating Curve= 0 ,0
Exp/Cntr=0.3,0.1

Chan Stop Cuts=-1
Use User Specified Reach Order=0